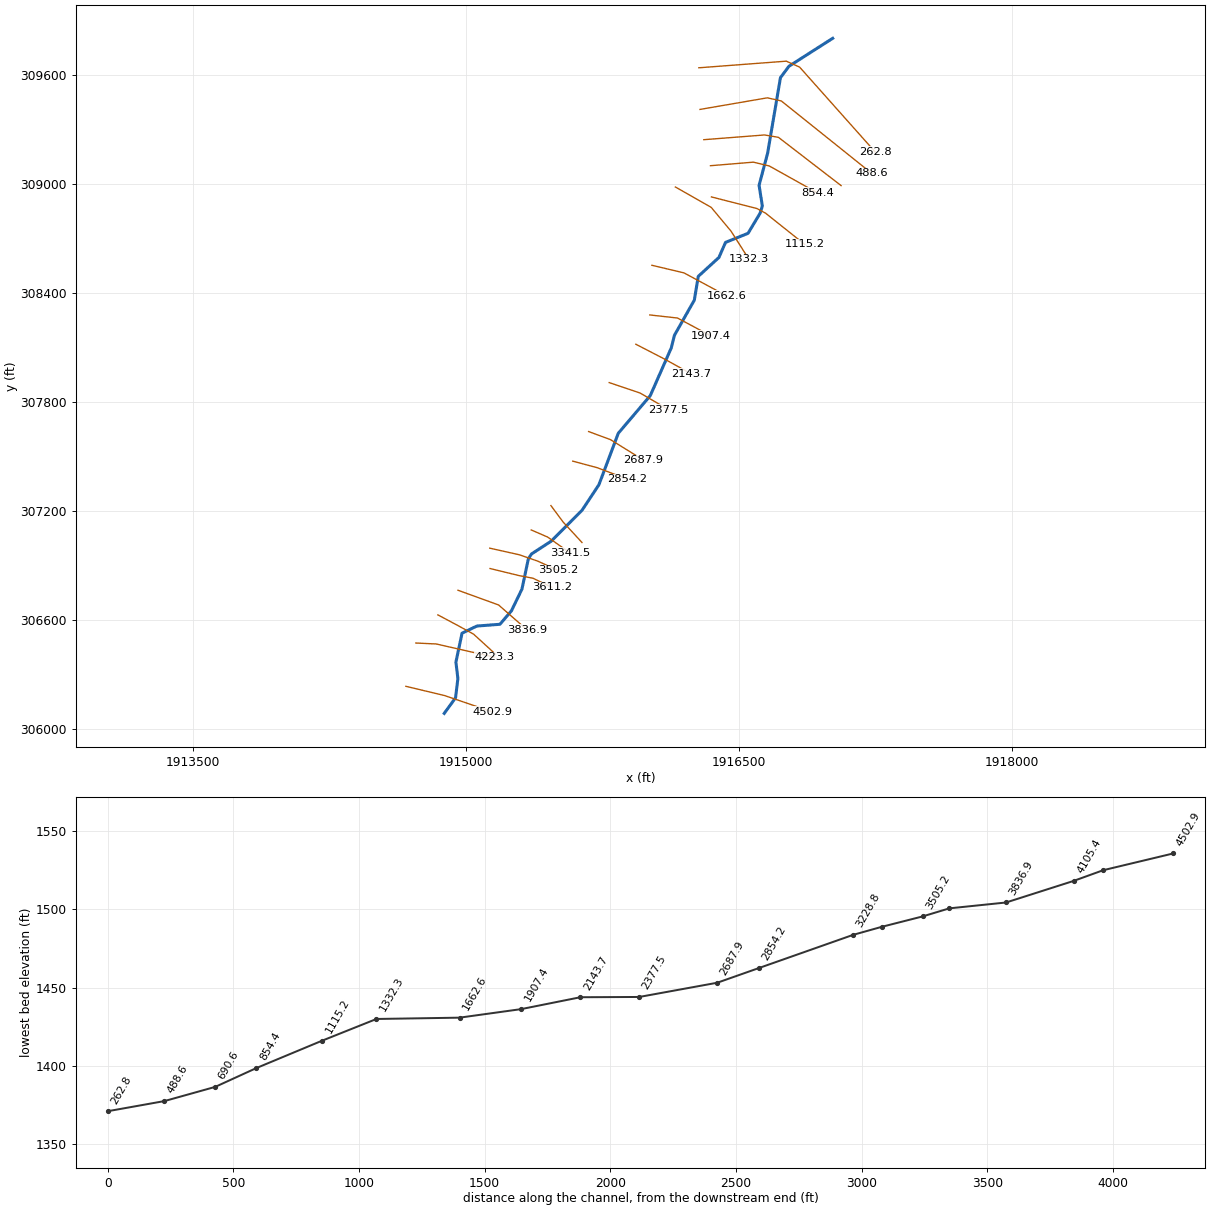
--- NP13.prj (project) ---

Proj Title=NP13
Current Plan=p01
Default Exp/Contr=0,0
English Units
Geom File=g01
Flow File=f01
Plan File=p01
BEGIN DESCRIPTION:
END DESCRIPTION:
DSS Export Rating Curves= 0
DSS Export Rating Curve Sorted= 0
DSS Export Volume Flow Curves= 0
DXF OffsetX= 0
DXF OffsetY= 0
DXF ScaleX= 0
DXF ScaleY= 0

--- NP13.p01 (plan) ---

Plan Title=Floodplain
Program Version=4.00
Geom File=g01
Flow File=f01
K Sum by GR=0
Std Step Tol=0.01
Critical Tol=0.01
Num of Std Step Trials=20
Max Error Tol=0.3
Flow Tol Ratio=0.001
Split Flow NTrial=30
Split Flow Tol=0.02
Split Flow Ratio=0.02
Log Output Level=0
Friction Slope Method=1
Unsteady Friction Slope Method=2
Unsteady Bridges Friction Slope Method=1
Global Log Level=0
CheckData=False
Run HTab=0
Run UNet=0
Run PostProcess=0
UNET Theta=0
UNET Theta Warmup=0
UNET ZTol=0
UNET ZSATol=0
UNET MxIter=0
UNET MaxInSteps=0
UNET DtIC=0
UNET DtMin=0
UNET MaxCRTS=0
UNET WFStab=0
UNET SFStab=0
UNET WFX=0
UNET SFX=0
UNET DSS MLevel=0
UNET DZMax Abort=0
UNET Convert EG Bridges=0
UNET Use Existing IB Tables=0
UNET Froude Limit=0
UNET Froude Power=0
Write IC File=0
Echo Input=False
Echo Output=False
Write Detailed=0

--- NP13.f01 (steady flow) ---

Flow Title=NFF Regression Equation
Program Version=4.10
Number of Profiles= 1
Profile Names=P100yr
River Rch & RM=NP13,Main            ,4502.9
527.9636
River Rch & RM=NP13,Main            ,262.8
581.0028
Boundary for River Rch & Prof#=NP13,Main            , 1
Up Type= 0
Dn Type= 3
Dn Slope=0.02944
DSS Import GetInterval= 0
DSS Import GetPeak= 0
DSS Import FillOption= 0

--- NP13.g01 (geometry) ---

Geom Title=USGS 10m DEM
Program Version=4.10

River Reach=NP13            ,Main
Reach XY= 30
     1914879.761      306085.044     1914941.824       306171.03
     1914954.642      306276.591      1914943.78      306367.162
     1914977.527      306526.495     1915058.798      306565.729
     1915185.751      306575.495     1915248.536       306649.05
     1915306.553      306769.093     1915342.001      306936.823
     1915359.362      306962.865     1915467.869      307033.394
      1915637.14       307203.75      1915729.37      307343.724
     1915835.707      307626.927     1916011.489      307834.175
     1916127.102      308097.476     1916143.867      308165.664
     1916253.459      308359.892     1916275.125      308490.794
      1916388.63      308594.889       1916424.9      308677.817
     1916548.598       308727.73     1916614.787      308838.407
     1916627.173      308878.077     1916609.112      308992.022
      1916656.02      309168.268     1916726.549      309584.392
     1916773.207      309647.327     1917013.369      309801.141

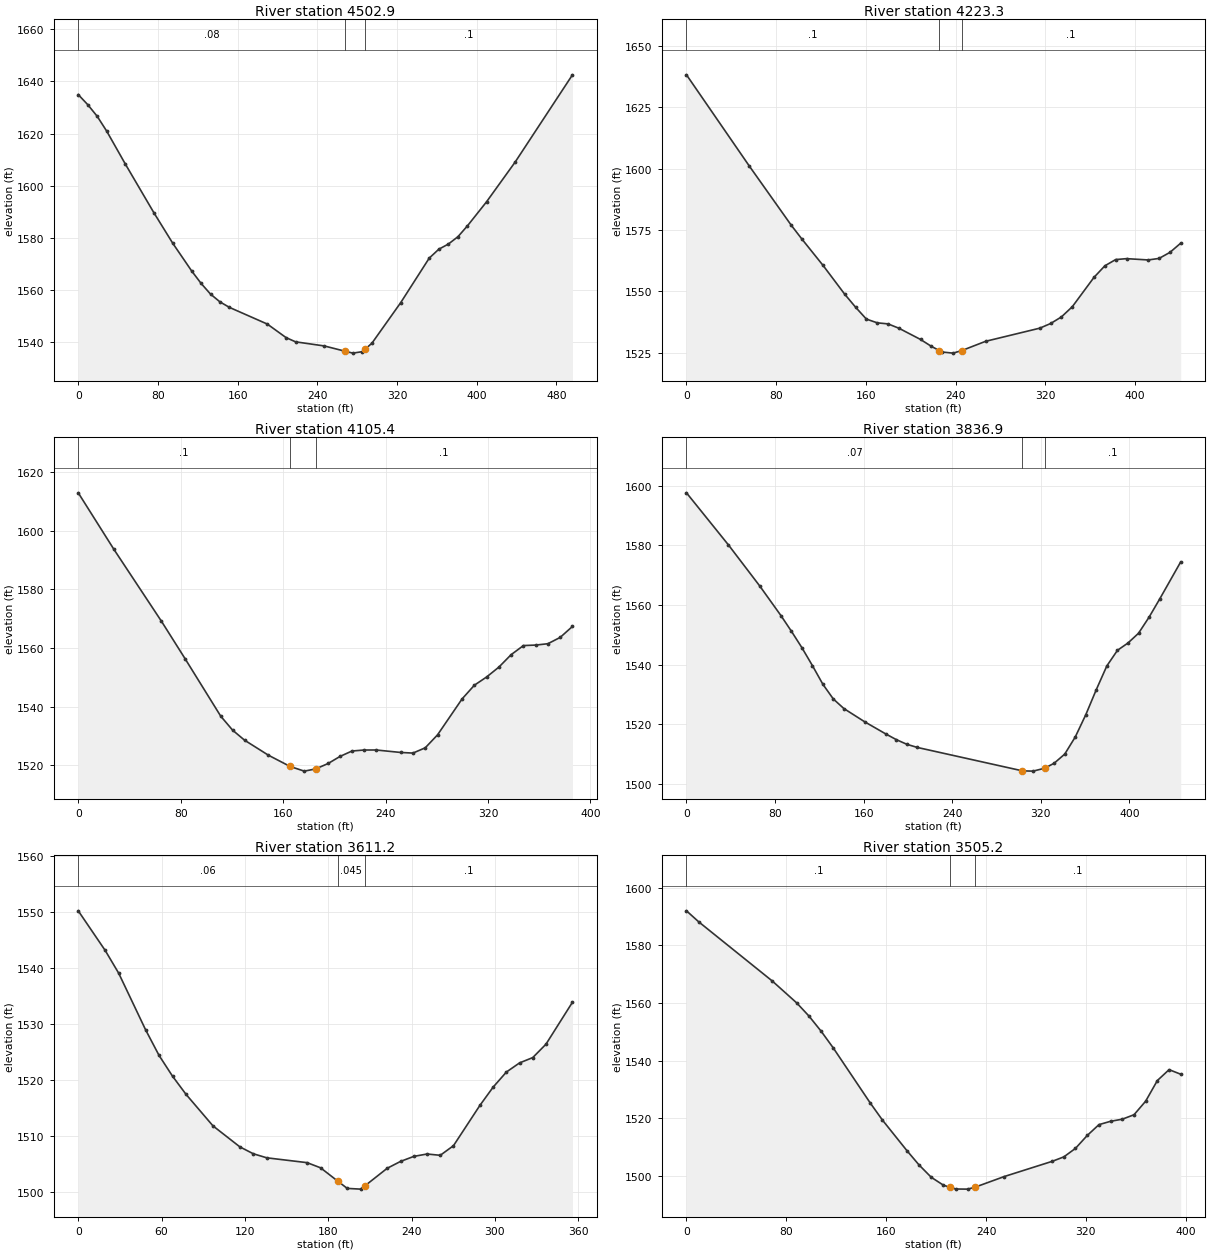
Type RM Length L Ch R = 1 ,4502.9  ,276.8,279.6,282.1
XS GIS Cut Line= 3
     1914668.968       306234.06     1914881.208      306183.278
     1915144.229      306093.435
#Sta/Elev= 30
       0 1634.96     9.5 1631.11      19 1626.64    28.5 1620.97    47.4  1608.2
    75.9  1589.6    94.9 1577.84   113.9 1567.19   123.4  1562.4   132.8 1558.32
   142.3 1555.32   151.8 1553.21   189.8 1546.81   208.7 1541.59   218.2 1539.98
     247  1538.4   267.8 1536.38   275.7 1535.64   285.3 1536.21   287.8 1537.06
   294.9 1539.48   323.7 1555.01   352.4 1572.15     362 1575.56   371.6 1577.54
   381.2 1580.36   390.8 1584.56   409.9 1593.76   438.7 1609.07   496.2 1642.56
#Mann= 3 , 0 , 0
       0     .08       0   267.8    .045       0   287.8      .1       0
Bank Sta=267.8,287.8
XS Rating Curve= 0 ,0
Exp/Cntr=0.3,0.1

Type RM Length L Ch R = 1 ,4223.3  ,124.7,117.9,113
XS GIS Cut Line= 3
     1914723.656      306472.341     1914835.635      306467.133
     1915155.947      306394.216
#Sta/Elev= 30
       0 1638.11      56 1601.01    93.4 1576.93   102.8 1571.36   121.8 1560.56
   141.1 1548.85   150.8 1543.56   160.4 1538.75   170.1 1537.23   179.7  1536.8
   189.4 1535.03   208.7 1530.46   218.4 1527.64   225.4 1525.97     228 1525.35
   237.7 1524.91   245.4 1525.95   266.7 1529.72     315 1535.07   324.7 1536.97
   334.3 1539.65     344 1543.81   363.3 1555.73     373 1560.43   382.6 1562.96
   392.3 1563.34   411.6 1562.81   421.3 1563.43     431 1565.89   440.6 1569.63
#Mann= 3 , 0 , 0
       0      .1       0   225.4    .045       0   245.4      .1       0
Bank Sta=225.4,245.4
XS Rating Curve= 0 ,0
Exp/Cntr=0.3,0.1

Type RM Length L Ch R = 1 ,4105.4  ,273.9,268.5,260.5
XS GIS Cut Line= 4
      1914844.75      306627.289     1914959.333      306566.091
     1915040.954      306521.077     1915161.156      306411.143
#Sta/Elev= 30
       0 1612.88    27.8 1593.65      65 1569.11    83.5 1556.32   111.3 1536.77
   120.6    1532   129.9  1528.6   148.5 1523.49   165.4 1519.66   176.5 1518.06
   185.4  1518.8   195.2 1520.67   204.5 1523.08   213.8 1524.91   223.1 1525.25
   232.7 1525.26   251.9 1524.42   261.4 1524.21     271    1526   280.6 1530.41
   299.8 1542.67   309.4 1547.34   318.9 1550.12   328.5 1553.49   338.1 1557.74
   347.7 1560.84   357.3 1561.01   366.8 1561.47   376.4 1563.62     386 1567.36
#Mann= 3 , 0 , 0
       0      .1       0   165.4    .045       0   185.4      .1       0
Bank Sta=165.4,185.4
XS Rating Curve= 0 ,0
Exp/Cntr=0.3,0.1

Type RM Length L Ch R = 1 ,3836.9  ,212.3,225.6,238.9
XS GIS Cut Line= 3
     1914955.427      306762.706     1915178.083      306681.976
     1915335.635      306543.956
#Sta/Elev= 30
       0 1597.66    37.9 1580.18    66.3 1566.34    85.3 1556.48    94.7 1551.26
   104.2 1545.73   113.7 1539.72   123.2 1533.42   132.6 1528.51   142.1 1525.31
     161 1520.84     180 1516.78   189.5 1514.87     199 1513.31   208.4 1512.26
   303.4  1504.4     313 1504.31   323.4 1505.28     332 1506.95   341.6 1510.03
   351.1 1515.78   360.6 1523.24   370.1 1531.66   379.6  1539.6   389.2 1544.84
   398.7 1547.29   408.2 1550.55   417.7 1555.93   427.3 1562.03   446.3 1574.49
#Mann= 3 , 0 , 0
       0     .07       0   303.4    .045       0   323.4      .1       0
Bank Sta=303.4,323.4
XS Rating Curve= 0 ,0
Exp/Cntr=0.3,0.1

Type RM Length L Ch R = 1 ,3611.2  ,109.6,106,102.4
XS GIS Cut Line= 4
     1915131.208      306882.497     1915291.364      306843.435
     1915366.885      306829.112      1915469.75      306779.633
#Sta/Elev= 30
       0 1550.18    19.4 1543.12    29.1 1539.07    48.5 1528.97    58.2  1524.4
    67.9  1520.7    77.6 1517.47      97 1511.85   116.4  1508.1   126.1 1506.87
   135.8 1506.15   164.8 1505.29   174.5 1504.37   186.7 1502.03   193.7  1500.7
   203.3 1500.57   206.7 1501.21   222.5 1504.29   232.1 1505.51   241.7 1506.41
   251.2 1506.83   260.7  1506.6   270.2 1508.31   289.3 1515.52   298.8 1518.76
   308.3 1521.44   317.8 1523.07   327.3 1524.02   336.8  1526.4   355.9 1533.89
#Mann= 3 , 0 , 0
       0     .06       0   186.7    .045       0   206.7      .1       0
Bank Sta=186.7,206.7
XS Rating Curve= 0 ,0
Exp/Cntr=0.3,0.1

Type RM Length L Ch R = 1 ,3505.2  ,170.9,163.7,156.5
XS GIS Cut Line= 4
     1915129.906      306994.476     1915292.666      306958.018
     1915394.229      306922.862     1915504.906      306872.081
#Sta/Elev= 30
       0 1592.01     9.8 1588.19    68.7 1567.67    88.3 1560.06    98.1 1555.51
   107.9 1550.23   117.7 1544.37   147.2 1525.35     157  1519.4   176.6  1508.8
   186.3 1503.84   196.1 1499.55   205.9 1496.79   211.4 1496.04   215.6 1495.47
   225.4 1495.43   231.4 1496.13   254.7 1499.81     293 1505.07   302.4 1506.63
   311.7 1509.58   321.1 1514.05   330.5 1517.81   339.8 1518.97   349.2  1519.7
   358.6 1521.25   367.9 1525.94   377.3 1533.12   386.7 1536.89     396 1535.31
#Mann= 3 , 0 , 0
       0      .1       0   211.4    .045       0   231.4      .1       0
Bank Sta=211.4,231.4
XS Rating Curve= 0 ,0
Exp/Cntr=0.3,0.1

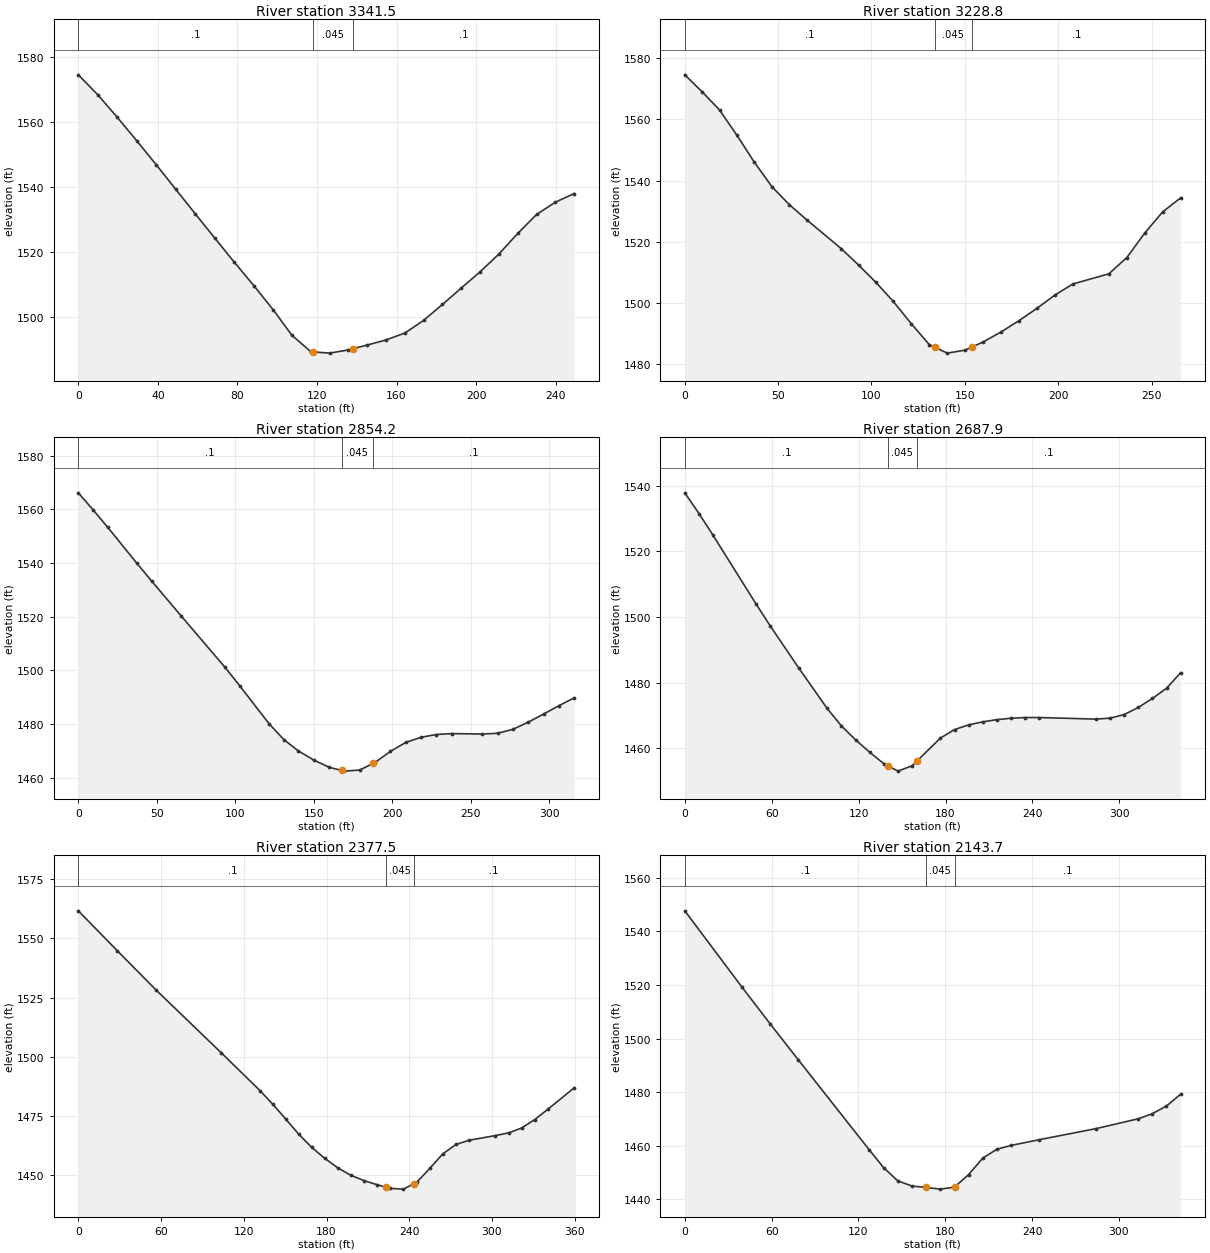
Type RM Length L Ch R = 1 ,3341.5  ,118,112.7,107.3
XS GIS Cut Line= 3
      1915357.77      307094.737     1915447.614      307055.674
     1915571.312      306968.435
#Sta/Elev= 29
       0 1574.65     9.8 1568.47    19.6 1561.52    29.4 1554.28    39.2 1546.87
      49  1539.3    58.8 1531.74    68.6 1524.26    78.4 1516.82    88.2 1509.61
      98  1502.1   107.4 1494.24   116.9 1489.18   118.1 1489.12   126.4 1488.74
   135.8 1489.74   138.1 1490.11   145.3 1491.25   154.7  1492.8   164.2 1494.94
   173.6 1498.84   183.1 1503.77   192.6 1508.86     202 1513.83   211.5 1519.36
     221 1525.73   230.4 1531.54   239.9 1535.35   249.3    1538
#Mann= 3 , 0 , 0
       0      .1       0   118.1    .045       0   138.1      .1       0
Bank Sta=118.1,138.1
XS Rating Curve= 0 ,0
Exp/Cntr=0.3,0.1

Type RM Length L Ch R = 1 ,3228.8  ,362.9,374.7,386.1
XS GIS Cut Line= 3
     1915465.843      307228.851      1915532.25      307139.008
     1915636.416      307025.726
#Sta/Elev= 29
       0 1574.58     9.3 1569.03    18.6 1563.11    27.9 1554.86    37.2 1546.08
    46.6  1538.1    55.9 1532.22    65.2 1527.28    83.8 1517.81    93.1 1512.43
   102.4 1506.78   111.7 1500.54   121.3 1493.29     131 1486.43   133.9  1485.6
   140.6 1483.67   150.2 1484.65   153.9 1485.68   159.8 1487.31   169.4 1490.58
     179 1494.27   188.7 1498.33   198.3 1502.66   207.9 1506.26   227.1 1509.56
   236.8  1514.9   246.4  1522.9     256 1529.83   265.6 1534.38
#Mann= 3 , 0 , 0
       0      .1       0   133.9    .045       0   153.9      .1       0
Bank Sta=133.9,153.9
XS Rating Curve= 0 ,0
Exp/Cntr=0.3,0.1

Type RM Length L Ch R = 1 ,2854.2  ,170.6,166.2,161.3
XS GIS Cut Line= 3
     1915585.635      307473.643     1915721.052      307437.185
     1915885.114      307374.685
#Sta/Elev= 30
       0 1566.19     9.4 1559.84    18.7 1553.37    37.4 1539.86    46.8 1533.25
    65.4 1520.39    93.5 1501.12   102.8  1494.3   121.5 1480.14   130.9 1474.24
   140.2    1470     150 1466.62   159.8 1463.92   167.7 1462.76   169.5  1462.5
   179.2  1462.9   187.7 1465.36     189 1465.74   198.8 1469.86   208.5 1473.18
   218.3 1475.12     228 1476.14   237.8 1476.48   257.3 1476.32     267  1476.6
   276.8 1478.08   286.5 1480.73   296.3 1483.75     306 1486.85   315.8  1489.8
#Mann= 3 , 0 , 0
       0      .1       0   167.7    .045       0   187.7      .1       0
Bank Sta=167.7,187.7
XS Rating Curve= 0 ,0
Exp/Cntr=0.3,0.1

Type RM Length L Ch R = 1 ,2687.9  ,310.1,310.4,311.1
XS GIS Cut Line= 3
     1915672.875      307636.403     1915792.666      307592.133
     1915974.958      307478.851
#Sta/Elev= 30
       0  1537.8     9.8  1531.5    19.6 1524.82    49.1 1504.04    58.9 1497.35
    78.6 1484.53    98.2 1472.22   108.1 1466.88   117.9 1462.62   127.7 1458.83
   137.5 1455.33   140.1 1454.73   147.2  1453.1     157 1454.75   160.1 1456.11
   176.5 1463.17   186.2 1465.75     196 1467.19   205.8 1468.11   215.5 1468.77
   225.3  1469.2     235 1469.41   244.8 1469.41   283.8 1468.93   293.6 1469.23
   303.3 1470.32   313.1 1472.48   322.8 1475.21   332.6 1478.33   342.3 1483.05
#Mann= 3 , 0 , 0
       0      .1       0   140.1    .045       0   160.1      .1       0
Bank Sta=140.1,160.1
XS Rating Curve= 0 ,0
Exp/Cntr=0.3,0.1

Type RM Length L Ch R = 1 ,2377.5  ,232.4,233.8,234.2
XS GIS Cut Line= 3
     1915786.156      307905.935     1915955.427      307848.643
     1916111.677      307757.497
#Sta/Elev= 29
       0 1561.65    28.2 1544.82    56.4 1528.17   103.5 1501.74   131.7  1485.7
   141.1 1479.86   150.5 1473.59   159.9 1467.21   169.3 1461.65   178.7 1457.04
   188.2 1452.99   197.7 1449.85   207.3 1447.61   216.8 1445.86   223.3 1444.81
   226.3 1444.32   235.8 1444.02   243.3 1446.28   245.4 1446.91   254.9 1452.78
   264.4 1458.96   273.9  1462.9   283.4 1464.68   302.5 1466.66     312 1467.79
   321.5 1469.85     331 1473.42   340.6 1477.82   359.6 1486.82
#Mann= 3 , 0 , 0
       0      .1       0   223.3    .045       0   243.3      .1       0
Bank Sta=223.3,243.3
XS Rating Curve= 0 ,0
Exp/Cntr=0.3,0.1

Type RM Length L Ch R = 1 ,2143.7  ,236.5,236.3,236.5
XS GIS Cut Line= 3
     1915932.164      308117.211     1916088.973      308036.043
     1916234.072      307955.414
#Sta/Elev= 22
       0  1547.7    39.2 1519.44    58.9 1505.59    78.5 1492.05   127.5 1458.48
   137.3 1451.92   147.1 1446.95     157    1445   166.6  1444.5   176.6 1443.85
   186.3 1444.59   186.6 1444.73   196.1 1449.27   205.9 1455.42   215.6 1458.72
   225.4 1460.16   244.9  1462.3     284 1466.41   313.3  1470.1     323 1471.98
   332.8 1474.86   342.6 1479.27
#Mann= 3 , 0 , 0
       0      .1       0   166.6    .045       0   186.6      .1       0
Bank Sta=166.6,186.6
XS Rating Curve= 0 ,0
Exp/Cntr=0.3,0.1

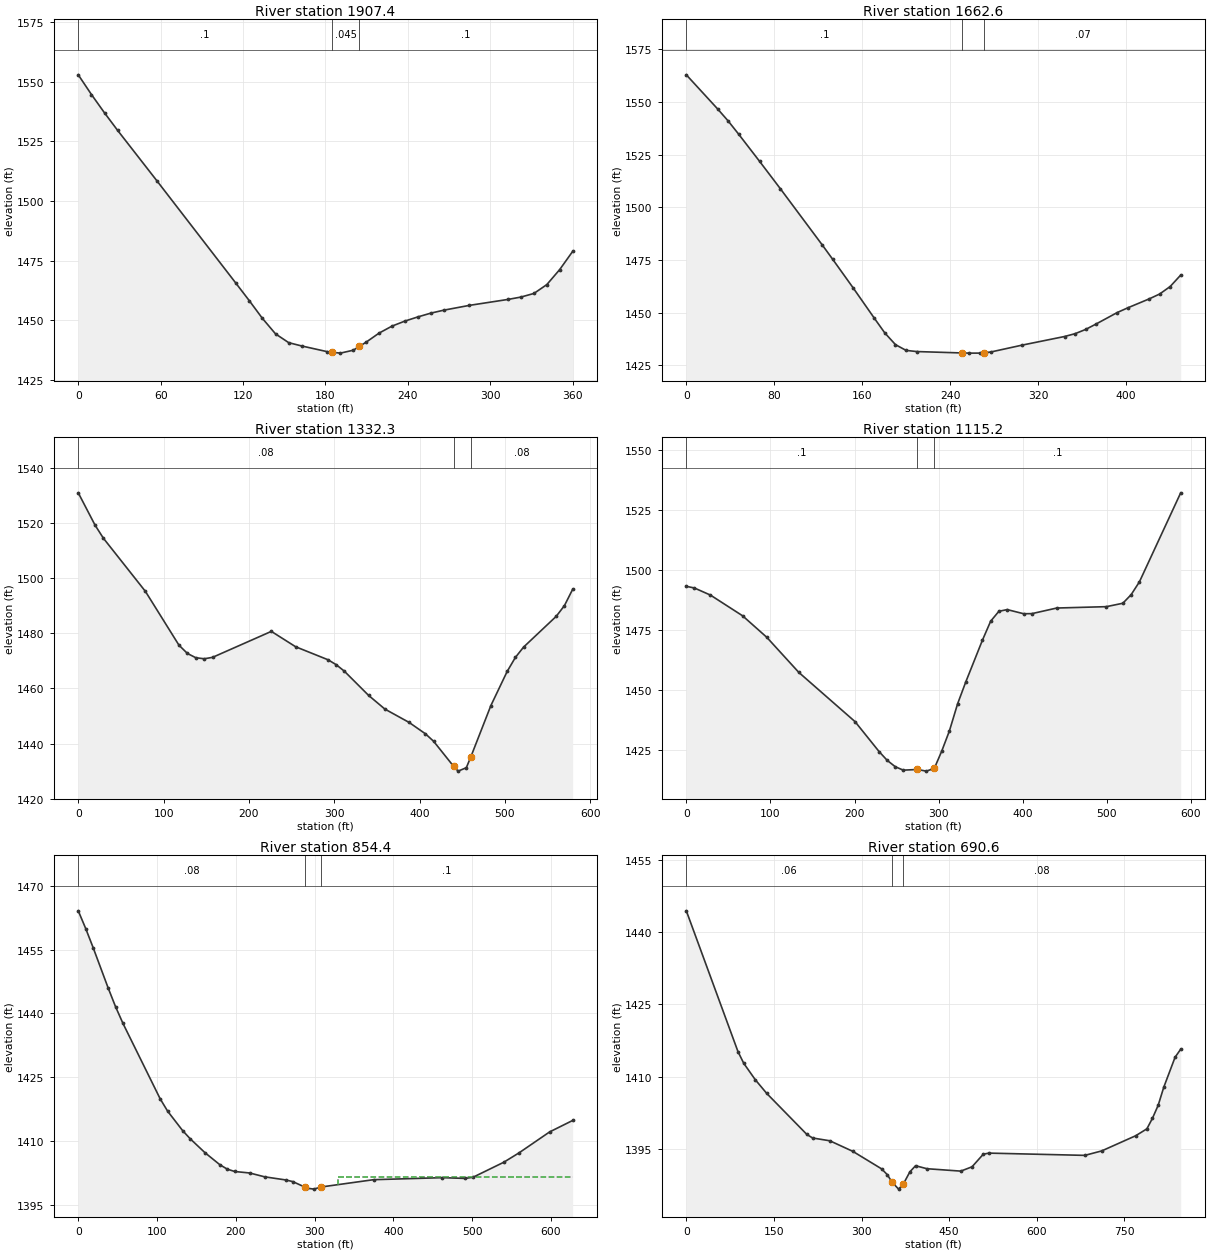
Type RM Length L Ch R = 1 ,1907.4  ,244.7,244.8,244.5
XS GIS Cut Line= 3
     1916008.812      308278.331     1916161.156      308261.403
     1916343.447      308163.747
#Sta/Elev= 30
       0 1552.92     9.6 1544.67    19.2 1536.91    28.7 1529.61    57.5 1508.33
     115 1465.44   124.5  1458.3   134.1 1450.84   143.7 1444.32   153.3 1440.63
   162.7 1439.26   181.5 1436.84   184.7 1436.64   190.9 1436.25   200.3 1437.47
   204.7 1439.05   209.7 1440.85   219.1 1444.64   228.5 1447.57   237.9 1449.68
   247.3 1451.42   256.7    1453   266.1 1454.24   284.9 1456.27   313.1 1458.77
   322.5 1459.76   331.9 1461.27   341.3 1464.98   350.7  1471.3   360.1 1478.88
#Mann= 3 , 0 , 0
       0      .1       0   184.7    .045       0   204.7      .1       0
Bank Sta=184.7,204.7
XS Rating Curve= 0 ,0
Exp/Cntr=0.3,0.1

Type RM Length L Ch R = 1 ,1662.6  ,343,330.4,316.2
XS GIS Cut Line= 3
     1916020.531      308551.768     1916196.312      308510.101
     1916433.291      308382.497
#Sta/Elev= 30
       0 1562.94    28.5 1546.74      38 1541.08    47.5 1534.84    66.6 1521.91
    85.6 1508.84   123.6 1482.23   133.1 1475.42   152.1 1461.56   171.1 1447.36
   180.6 1440.39   190.3 1434.84   199.9 1432.12   209.5 1431.56     251 1430.89
   257.6 1430.81   267.2 1430.82     271 1431.02   276.8 1431.32   305.6 1434.62
   344.1  1438.7   353.7 1440.04   363.3 1442.05   372.9 1444.66   392.1 1450.09
   401.7 1452.33     421 1456.53   430.6 1458.86   440.2 1462.42   449.8 1467.86
#Mann= 3 , 0 , 0
       0      .1       0     251    .045       0     271     .07       0
Bank Sta=251,271
XS Rating Curve= 0 ,0
Exp/Cntr=0.3,0.1

Type RM Length L Ch R = 1 ,1332.3  ,204.1,217.1,229.7
XS GIS Cut Line= 4
     1916149.437      308982.758     1916346.052      308870.778
     1916455.427      308739.268     1916553.083      308585.622
#Sta/Elev= 30
       0 1531.06    19.7 1519.31    29.5 1514.55    78.7 1495.26     118 1475.73
   127.9 1472.72   137.7 1471.17   147.6 1470.78   157.4  1471.3   226.3 1480.73
   254.8 1475.14   292.8 1470.41   302.3 1468.63   311.8 1466.29   340.3 1457.47
   359.3 1452.52   387.8 1447.65   406.9 1443.52   416.5  1440.8     440 1431.67
   445.2 1429.97   454.8 1431.21     460 1435.09   483.6  1453.8   502.7  1466.2
   512.3 1471.27   521.9 1475.02   560.2 1486.21   569.8  1490.1   579.4    1496
#Mann= 3 , 0 , 0
       0     .08       0     440    .045       0     460     .08       0
Bank Sta=440,460
XS Rating Curve= 0 ,0
Exp/Cntr=0.3,0.1

Type RM Length L Ch R = 1 ,1115.2  ,253.6,260.7,267.1
XS GIS Cut Line= 4
     1916347.354       308928.07     1916597.354      308864.268
     1916645.531      308838.226     1916860.375      308666.351
#Sta/Elev= 30
       0 1493.05     9.6 1492.35    28.7 1489.39    66.9 1480.77    95.6 1471.84
   133.8 1457.18   200.7 1436.66   229.3 1424.18   238.9 1420.54   248.5 1417.89
     258 1416.47   274.9 1416.74   285.4 1416.06   294.9  1417.2   303.6 1424.28
   312.8 1432.75   322.6  1444.1   332.4 1453.29   352.1 1470.58   361.9 1478.51
   371.7 1482.64   381.6 1483.35   401.2 1481.62     411 1481.67   440.5    1484
   499.5 1484.57   519.1 1485.99     529 1489.58   538.8  1494.9   587.9 1531.99
#Mann= 3 , 0 , 0
       0      .1       0   274.9    .045       0   294.9      .1       0
Bank Sta=274.9,294.9
XS Rating Curve= 0 ,0
Exp/Cntr=0.3,0.1

Type RM Length L Ch R = 1 ,854.4   ,162.2,163.8,165.4
XS GIS Cut Line= 4
     1916342.145      309099.945     1916577.822      309119.476
     1916665.062      309098.643     1916928.083      308951.508
#Sta/Elev= 30
       0 1464.15     9.5 1459.96    18.9 1455.48    37.8 1446.07    47.3  1441.6
    56.8 1437.63     104 1419.89   113.5 1416.98   132.4 1412.44   141.9 1410.53
   160.8 1407.23   179.7 1404.39   189.2 1403.34   198.6 1402.79   217.6 1402.44
   236.5 1401.54   263.4  1400.8   272.4 1400.41   287.8  1399.1   290.3 1398.87
   299.3 1398.64   307.8 1399.13   374.8 1400.86   462.3 1401.34   491.4 1401.16
   501.2 1401.44   540.1 1404.96   559.5 1407.17   598.4 1412.11   627.6  1414.8
#Mann= 3 , 0 , 0
       0     .08       0   287.8    .045       0   307.8      .1       0
#XS Ineff= 2 , 0
                          330.03         1401.52
Permanent Ineff=
       F       F
Bank Sta=287.8,307.8
XS Rating Curve= 0 ,0
Exp/Cntr=0.3,0.1

Type RM Length L Ch R = 1 ,690.6   ,203.2,202,200.7
XS GIS Cut Line= 4
     1916305.687      309243.174      1916639.02      309269.216
     1916715.612       309256.14     1917059.593       308990.57
#Sta/Elev= 30
       0 1444.42    88.5 1415.17    98.3 1412.76     118 1409.36   137.7  1406.5
   206.5 1397.97   216.3 1397.24   245.8 1396.66   285.2 1394.46   334.4 1390.83
   344.1 1389.63   351.8 1388.16   363.5 1386.62   371.8 1387.72   382.9 1390.22
   392.6 1391.48     412 1390.86     470 1390.36   489.3 1391.26   508.6 1393.88
   518.3  1394.1   682.4 1393.63   711.4 1394.56   769.4  1397.7   788.7 1399.14
   798.3 1401.35     808 1404.02   817.6 1407.78     837 1414.02   846.6 1415.68
#Mann= 3 , 0 , 0
       0     .06       0   351.8    .045       0   371.8     .08       0
Bank Sta=351.8,371.8
XS Rating Curve= 0 ,0
Exp/Cntr=0.3,0.1

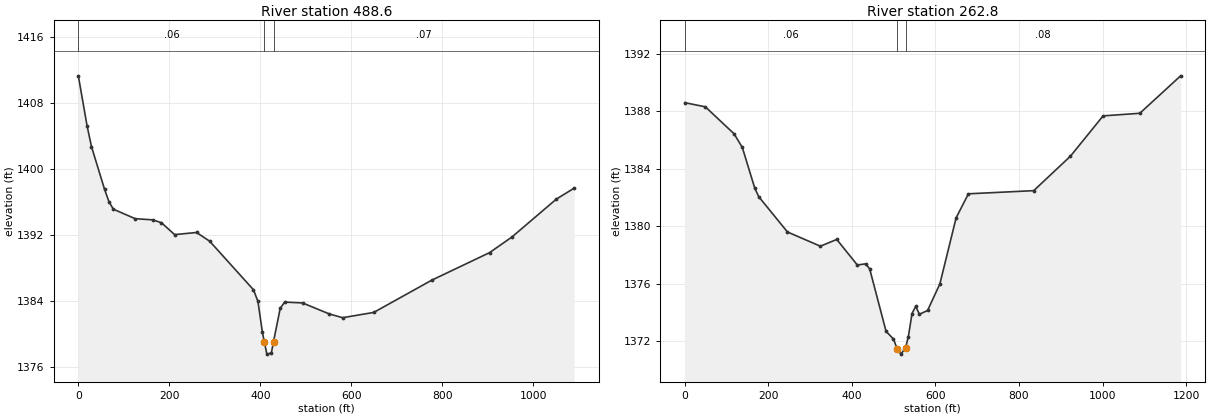
Type RM Length L Ch R = 1 ,488.6   ,229.4,225.8,222.1
XS GIS Cut Line= 4
     1916284.854      309409.841     1916654.645      309473.643
     1916731.209      309456.533     1917227.562      309058.278
#Sta/Elev= 30
       0 1411.27    19.2 1405.22    28.9  1402.7    57.7 1397.52    67.4 1396.02
      77 1395.12   125.1 1393.97   163.6 1393.83   182.8 1393.48   211.7 1392.04
   259.8  1392.3   288.7 1391.25   385.1 1385.36   394.9 1383.95   404.7  1380.2
   409.1 1379.02   414.5 1377.57   424.3 1377.71   429.1 1379.08   443.9 1383.13
   453.7 1383.87   492.9 1383.77   551.6 1382.44     581 1381.98   649.5 1382.62
   776.8 1386.52   904.1 1389.86     953 1391.74  1050.9 1396.34  1090.1 1397.67
#Mann= 3 , 0 , 0
       0     .06       0   409.1    .045       0   429.1     .07       0
Bank Sta=409.1,429.1
XS Rating Curve= 0 ,0
Exp/Cntr=0.3,0.1

Type RM Length L Ch R = 1 ,262.8   ,267.4,262.8,258.4
XS GIS Cut Line= 4
     1916278.343      309639.008     1916758.812      309675.466
     1916831.729      309642.914     1917247.093      309175.466
#Sta/Elev= 30
       0 1388.61    49.2 1388.32     118 1386.44   137.7 1385.49   167.2 1382.68
     177 1382.06   245.8  1379.6   324.5 1378.61   363.8 1379.08     413  1377.3
   432.7 1377.38   442.5 1377.04   481.8 1372.68   499.6 1372.14   508.5 1371.45
   517.3 1371.09   528.5 1371.53   535.1 1372.29     544 1373.92   552.8 1374.42
   561.7 1373.87   581.2 1374.13   610.6 1375.98   649.6 1380.59     679 1382.26
   835.3 1382.48   923.2 1384.88  1001.4 1387.69  1089.3 1387.87    1187 1390.48
#Mann= 3 , 0 , 0
       0     .06       0   508.5    .045       0   528.5     .08       0
Bank Sta=508.5,528.5
XS Rating Curve= 0 ,0
Exp/Cntr=0.3,0.1

Chan Stop Cuts=-1
Use User Specified Reach Order=0
Composite Channel Slope=5